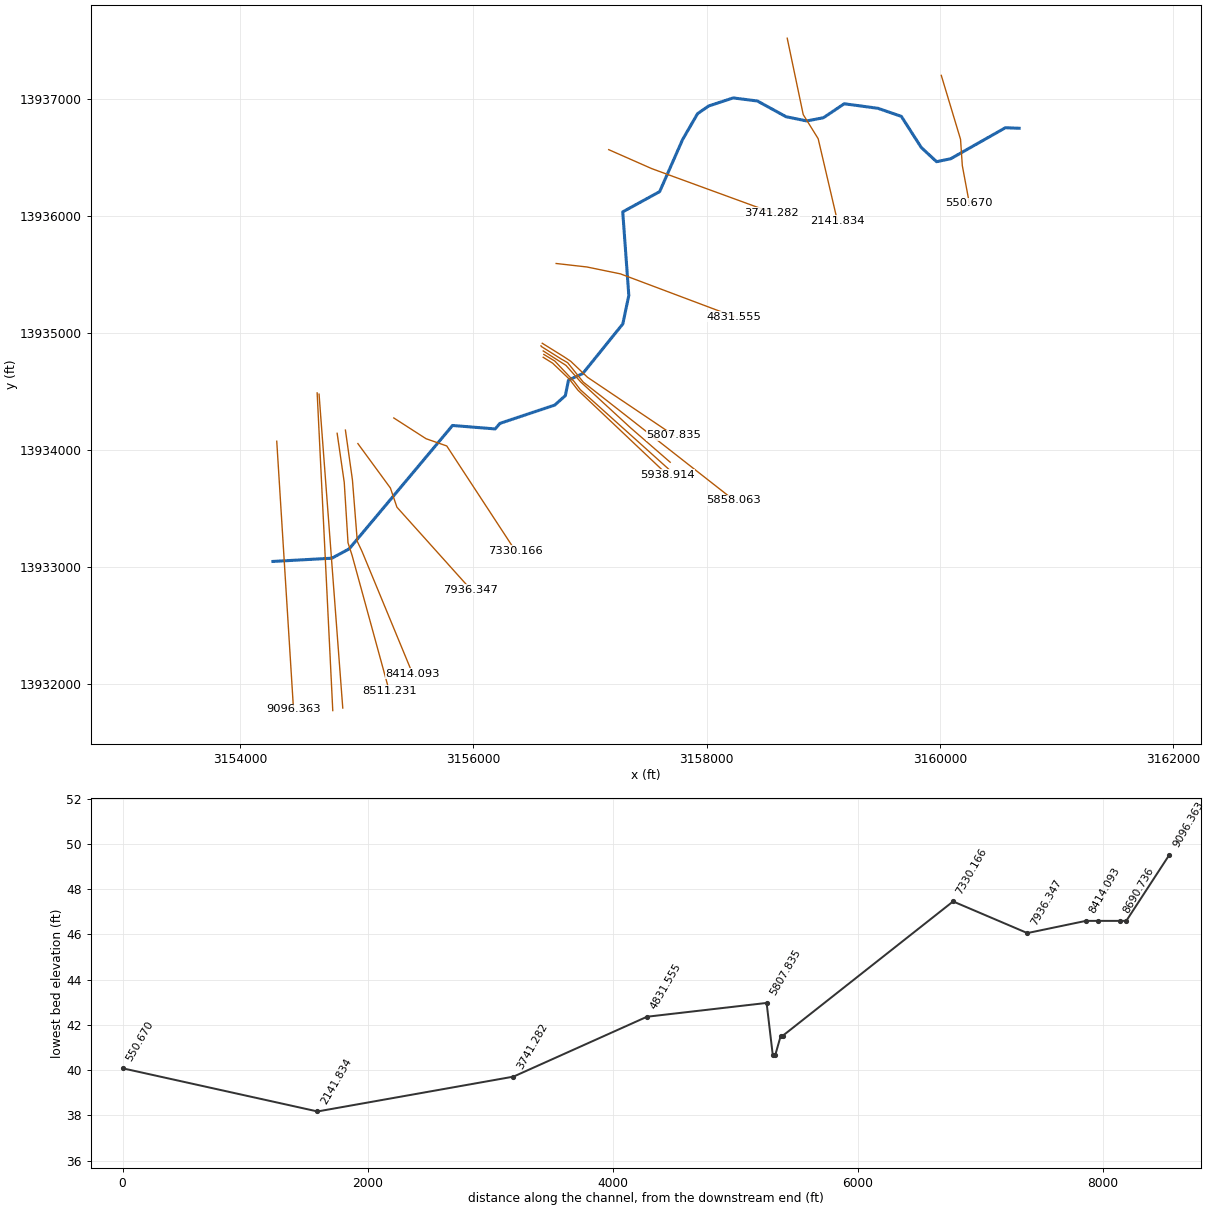
--- G103-44-00.prj (project) ---

Proj Title=G103-44-00
Current Plan=p03
Default Exp/Contr=.3,.1
English Units
Geom File=g03
Flow File=f01
Flow File=f02
Plan File=p01
Plan File=p03
Y Axis Title=Elevation
X Axis Title(PF)=Main Channel Distance
X Axis Title(XS)=Station
BEGIN DESCRIPTION:
San Jacinto River Watershed
TxDOT Ditch #4
HCFCD Unit G103-44-00
(Flood Hazard) Model
10, 2, 1, 0.2% Event
Filename g1034400.prj
Prepared by:  FTN Associates Ltd.   DATE:  May 2003
Reviewed by:     DATE:
STATUS (FINAL RAS)
Channel Slope: The low point elevations at river stations 2141.834 and RS 3741.282 were used to calculate the channel slope of 0.0009628 ft/ft.
END DESCRIPTION:
DSS Export Rating Curves= 0
DSS Export Rating Curve Sorted= 0
DSS Export Volume Flow Curves= 0
DXF OffsetX= 0
DXF OffsetY= 0
DXF ScaleX= 1
DXF ScaleY= 10

--- G103-44-00.p03 (plan) ---

Plan Title=Floodway
Version=Version 3.0.1  Mar 2001
Short Identifier=Floodway0607
Geom File=g03
Flow File=f02
Subcritical Flow
K Sum by GR= 0
Std Step Tol= 0.01
Critical Tol= 0.01
Num of Std Step Trials= 20
Max Error Tol= 0.3
Flow Tol Ratio= 0.001
Split Flow NTrial= 30
Split Flow Tol= 0.02
Split Flow Ratio= 0.02
Log Output Level= 0
Friction Slope Method= 1
Unsteady Friction Slope Method= 2
Parabolic Critical Depth
Global Vel Dist= 0 , 0 , 0
Global Log Level= 0
CheckData=True
Encroach Param=-1 ,0,0, 2
Encroach River=G103-44-00
Encroach Reach=TxDOT Ditch 4
Encroach Node=9096.363
       1  313.35  370.61
Encroach Node=8743.858
       1  577.64  644.04
Encroach Node=8690.736
       1  937.72 1004.12
Encroach Node=8600.98
       1   937.8 1004.12
Encroach Node=8511.231
       1   937.8  1004.2
Encroach Node=8414.093
       1  879.49  945.89
Encroach Node=7936.347
       1  511.06  580.13
Encroach Node=7330.166
       1  401.67  468.35
Encroach Node=5938.914
       1  195.12  301.16
Encroach Node=5923.128
       1  202.17  318.82
Encroach Node=5900.985
       1  202.17  318.82
Encroach Node=5878.843
       1  232.55  360.82
Encroach Node=5858.063
       1  291.73  421.82
Encroach Node=5807.835
       1  306.85  442.39
Encroach Node=4831.555
       1  343.66   743.3
Encroach Node=3741.282
       1  485.37  584.84
Encroach Node=2141.834
       1  663.59     923
Encroach Node=550.670
       1  605.64  765.64
Encroach Reach=G103-44-00_0006
Encroach Node=9096.363
       1  313.35  370.61
Encroach Node=8743.858
       1  577.64  644.04
Encroach Node=8690.736
       1  937.72 1004.12
Encroach Node=8600.98
       1   937.8 1004.12
Encroach Node=8511.231
       1   937.8  1004.2
Encroach Node=8414.093
       1  879.49  945.89
Encroach Node=7936.347
       1  511.06  580.13
Encroach Node=7330.166
       1  401.67  468.35
Encroach Node=5938.914
       1  195.12  301.16
Encroach Node=5923.128
       1  202.17  318.82
Encroach Node=5900.985
       1  202.17  318.82
Encroach Node=5878.843
       1  232.55  360.82
Encroach Node=5858.063
       1  291.73  421.82
Encroach Node=5807.835
       1  306.85  442.39
Encroach Node=4831.555
       1  343.66   743.3
Encroach Node=3741.282
       1  485.37  584.84
Encroach Node=2141.834
       1  663.59     923
Encroach Node=550.670
       1  605.64  765.64
Computation Interval=1HOUR
Output Interval=1HOUR
Run HTab= 0
Run UNet= 0
Run PostProcess= 0
UNET Theta= 1
UNET ZTol= 0.02
UNET ZSATol= 0.1
UNET MxIter= 20
UNET MaxInSteps= 20
UNET DtIC= 0
UNET DtMin= 0
UNET MaxCRTS= 20
UNET WFStab= 2
UNET SFStab= 1
UNET WFX= 1
UNET SFX= 1
UNET Convert EG Bridges=-1
UNET Use Existing IB Tables=-1
Instantaneous Interval=1HOUR
Write IC File= 0
Write Velocity= 0
Write Detailed= 0

--- G103-44-00.p01 (plan) ---

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Plan Title=FEMA Effective June 2007
Short Identifier=FEMAeff0607
Geom File=g03
Flow File=f01
Encroach Param=-1 ,0,0, 0

--- G103-44-00.f02 (steady flow) ---

Flow Title=Floodway
Version=Version 3.0.1  Mar 2001
Number of Profiles= 2
Profile Names=1PCT_100yr, 1PCTFloodway_100yrFW
River Rch & RM=G103-44-00,G103-44-00_0006   ,9096.363
    1005    1005
River Rch & RM=G103-44-00,G103-44-00_0006   ,8743.858
    1042    1042
River Rch & RM=G103-44-00,G103-44-00_0006   ,8690.736
    1178    1178
River Rch & RM=G103-44-00,G103-44-00_0006   ,8511.231
    1225    1225
River Rch & RM=G103-44-00,G103-44-00_0006   ,7936.347
    1277    1277
River Rch & RM=G103-44-00,G103-44-00_0006   ,7330.166
    1405    1405
River Rch & RM=G103-44-00,G103-44-00_0006   ,5938.914
    1417    1417
River Rch & RM=G103-44-00,G103-44-00_0006   ,5807.835
    1516    1516
River Rch & RM=G103-44-00,G103-44-00_0006   ,4831.555
    1633    1633
River Rch & RM=G103-44-00,G103-44-00_0006   ,3741.282
    1822    1822
River Rch & RM=G103-44-00,G103-44-00_0006   ,2141.834
    2032    2032
Boundary for River Rch & Prof#=G103-44-00,G103-44-00_0006   , 1
Up Type= 0
Dn Type= 3
Dn Slope=.0009628
DSS Import GetInterval= 0
DSS Import GetPeak= 0
DSS Import FillOption= 0

--- G103-44-00.f01 (steady flow) ---

Flow Title=FEMA Effective June 2007
Version=Version 3.0.1  Mar 2001
Number of Profiles= 4
Profile Names=10PCT_10yr, 2PCT_50yr, 1PCT_100yr, 0.2PCT_500yr
River Rch & RM=G103-44-00,G103-44-00_0006   ,9096.363
     637     880    1005    1337
River Rch & RM=G103-44-00,G103-44-00_0006   ,8743.858
     661     912    1042    1385
River Rch & RM=G103-44-00,G103-44-00_0006   ,8690.736
     747    1031    1178    1566
River Rch & RM=G103-44-00,G103-44-00_0006   ,8511.231
     773    1071    1225    1632
River Rch & RM=G103-44-00,G103-44-00_0006   ,7936.347
     802    1116    1277    1706
River Rch & RM=G103-44-00,G103-44-00_0006   ,7330.166
     873    1225    1405    1887
River Rch & RM=G103-44-00,G103-44-00_0006   ,5938.914
     880    1235    1417    1905
River Rch & RM=G103-44-00,G103-44-00_0006   ,5807.835
     934    1319    1516    2045
River Rch & RM=G103-44-00,G103-44-00_0006   ,4831.555
     998    1419    1633    2213
River Rch & RM=G103-44-00,G103-44-00_0006   ,3741.282
    1099    1579    1822    2486
River Rch & RM=G103-44-00,G103-44-00_0006   ,2141.834
    1211    1756    2032    2790
Boundary for River Rch & Prof#=G103-44-00,G103-44-00_0006   , 1
Up Type= 0
Dn Type= 3
Dn Slope=.0009628
DSS Import GetInterval= 0
DSS Import GetPeak= 0
DSS Import FillOption= 0

--- G103-44-00.g03 (geometry) ---

Geom Title=G103-44-00 June 2007
Version=Version 3.0.1  Mar 2001

River Reach=G103-44-00      ,G103-44-00_0006
Reach XY= 30
     3154282.626    13933047.735      3154788.05    13933075.373
      3154935.86    13933154.842     3155821.958    13934210.031
      3156187.41    13934180.517     3156228.307    13934227.911
     3156698.323    13934384.424     3156788.678    13934465.008
     3156816.349     13934598.08     3156937.966    13934653.486
     3157281.356    13935077.875     3157332.848    13935321.738
     3157280.841    13936036.039     3157597.244    13936209.036
     3157793.657    13936653.848     3157921.996    13936875.461
     3158017.294    13936941.167     3158227.608    13937010.158
     3158434.635    13936983.875     3158681.096    13936849.179
     3158858.549     13936813.04     3159001.048    13936840.924
     3159179.133    13936960.169     3159468.029    13936921.399
     3159668.485    13936852.408     3159839.364    13936586.299
     3159970.512    13936464.959     3160091.336    13936490.006
     3160560.746    13936755.462     3160678.135    13936750.548

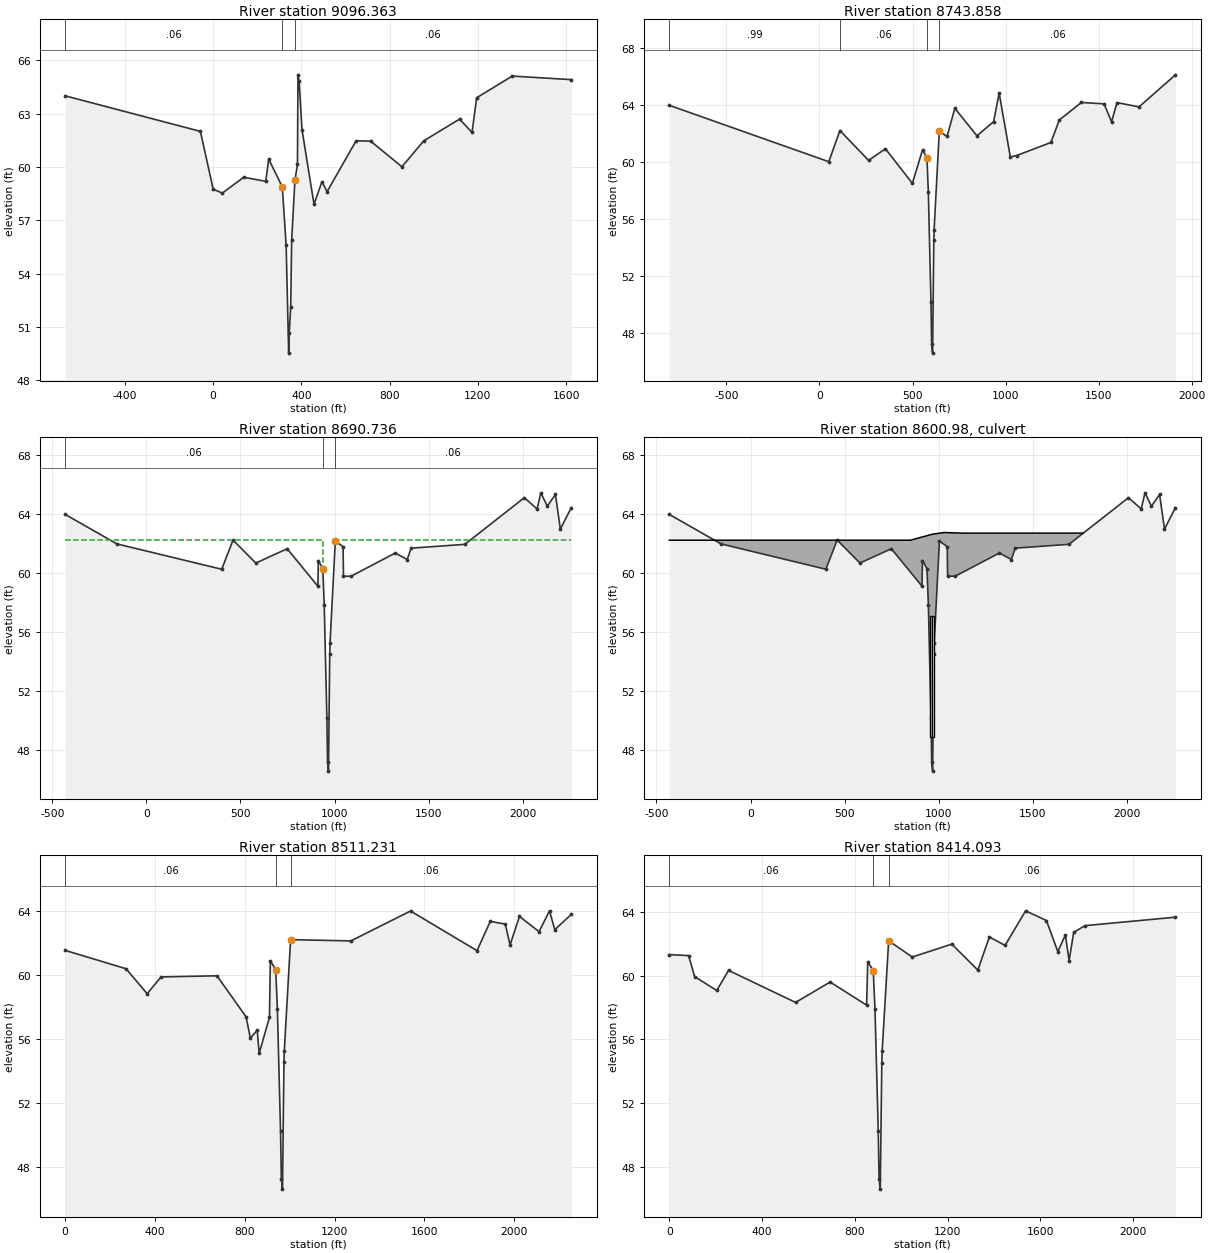
Type RM Length L Ch R = 1 ,9096.363,343.59,352.51,351.8
BEGIN DESCRIPTION:
423v1
Notes: Extended LOB to elev 64' at distance of 671.30'
May require psmoothing on near ROB - possibly not all effects of tree cover were removed in LIDAR here
Bank Station offset =      4658
The flow on ROB is not ineffective since the high points observed in this cross section is only a small cluster.
END DESCRIPTION:
XS GIS Cut Line= 4
 3154315.522643213934075.3221756 3154357.5321228 13933405.337939
 3154399.541602313932735.3537025 3154459.1349962 13931784.934061
#Sta/Elev= 30
  -671.3      64     -58      62       0   58.75   41.65   58.53  138.27   59.42
  238.35   59.19  251.68   60.44  313.35   58.88  330.76    55.6  342.31   49.53
  344.77   50.68   351.5    52.1  355.73   55.88  370.61   59.26  382.06   60.14
  384.42   65.18  389.63   64.81  402.64    62.1  457.14    57.9  493.25   59.17
   516.3   58.61     648   61.47  713.94   61.45  855.55   60.01   954.8   61.47
 1116.93   62.69 1173.49   61.94 1194.42   63.89 1355.83   65.11 1623.59   64.91
#Mann= 3 ,-1 , 0
  -671.3     .06       0  313.35    .035       0  370.61     .06       0
Bank Sta=313.35,370.61
XS Rating Curve= 0
Exp/Cntr=.3,.1

Type RM Length L Ch R = 1 ,8743.858,47.71,53.12,55.43
BEGIN DESCRIPTION:
423s1u.  Surveyed section.  XS 4/4
Notes: Extended LOB to elev 64' at distance of 806.84'
Bank Station offset =      4392
It is observed from the TIN that the high points in the ROB of this xsec are local and hence flow is not ineffective. Therefore n=0.99 not applied on the ROB.
END DESCRIPTION:
XS GIS Cut Line= 4
 3154661.8194145 13934488.720765 3154701.520695913933682.8580986
 3154741.221977313932876.9954321     3154795.637    13931772.471
#Sta/Elev= 30
 -806.84      64   50.28   60.04  110.16   62.23  264.17   60.13  354.62   60.95
  499.33   58.52   553.9   60.87  577.64   60.32  585.15   57.88  599.21   50.22
  602.83   47.24  607.84    46.6  614.47   54.52  616.05   55.26  644.04   62.19
  685.49   61.81  727.43   63.79   846.2   61.86  935.71   62.85  965.54   64.86
 1025.61   60.37 1058.91   60.47 1243.51   61.39 1288.75   62.97 1407.45    64.2
 1529.32    64.1 1569.59   62.84 1598.52   64.19 1716.95   63.89  1912.7   66.14
#Mann= 4 ,-1 , 0
 -806.84     .99       0  110.16     .06       0  577.64    .035       0
  644.04     .06       0
#Block Obstruct= 2 , 0
 -806.84                 1490.61 -806.84    64.3
Bank Sta=577.64,644.04
XS Rating Curve= 0
Exp/Cntr=.5,.3

Type RM Length L Ch R = 1 ,8690.736,164.72,179.51,201.18
BEGIN DESCRIPTION:
Copy of 423s1u.   XS 3/4.
Bank Station offset =      4390NOTES:  Adjusted elevations between CB's and changed contraction and expansion coefficients.  Extended LOB to elev 64' at distance of 790.15'.  Manning's 'n' in channel reduced u/s and d/s of culvert to help with negative changes in profile
END DESCRIPTION:
XS GIS Cut Line= 4
  3154678.16483213934477.5159607 3154737.829712913933689.6218288
 3154797.494593813932901.7276969     3154881.354    13931794.337
#Sta/Elev= 30
 -432.15      64 -157.03      62  400.47   60.28  460.44   62.26  581.58    60.7
  748.47   61.67  911.54   59.13  913.98   60.87  937.72   60.32  945.23   57.88
  959.29   50.22  962.91   47.24  967.92    46.6  974.55   54.52  976.13   55.26
 1004.12   62.19 1045.57   61.81 1047.63   59.81 1088.16   59.81 1323.02   61.38
 1386.44   60.94 1407.13   61.71 1692.95   61.97 2008.85   65.13 2076.72   64.37
 2096.78   65.46 2131.07   64.55 2174.32   65.35 2200.39      63 2258.71   64.46
#Mann= 3 , 0 , 0
 -432.15     .06       0  937.72    .035       0 1004.12     .06       0
#XS Ineff= 2 , 0
 -432.15  937.72   62.25 1004.12 -432.15   62.25
Permanent Ineff=
       F       F
#Block Obstruct= 2 , 0
 -432.15                 2008.85 -432.15   65.13
Bank Sta=937.72,1004.12
XS Rating Curve= 0
Exp/Cntr=.5,.3

Type RM Length L Ch R = 2 ,8600.98 ,,,
BEGIN DESCRIPTION:
423s1: Townsen Blvd (2- 8.3 x 8.2 Conc. Box Culverts)
NOTES: Extended road surface on left to x-sec sta 0 and on right to US x-sec sta 2198 & DS x-sec sta 3430.
Type of flow set to pressure/weir.
Length of box culverts determined using average of offset distances provided in survey data (Excel 423s1).  The survey points 5906, 5907, 5908, and 5909 were used for calculating the length of the culverts.
END DESCRIPTION:
Bridge Culvert--1,0,-1,-1, 0
Deck Dist Width WeirC Skew NumUp NumDn MinLoCord MaxHiCord MaxSubmerge Is_Ogee
71.71,36.1,2.6,0, 7, 7, 62.25, , .95, 0, 0,0,,
 -432.15  850.64  899.01  967.92 1027.83 1122.61 1765.85
   62.25   62.25   62.42   62.66   62.77   62.73   62.73
                                                        
       0 2256.56 2304.93 2373.84 2433.75 2528.53    3430
   62.25   62.25   62.42   62.66   62.77   62.73   62.73
                                                        
BR Coef=-1 , 0 , 0 ,, 0 ,,,.8,0,,0,
WSPro=,,,, 1 ,,,, 0 ,,,, 0 ,,,,-1 ,-1 ,-1 , 0 , 0 , 0 , 0 , 0
Multiple Barrel Culv=2,8.2,8.3,129.61,.012,.5,1,10,1,48.935,48.73, 2,Culvert #1  , 0 ,25.45
  960.22   961.8  970.62   972.2
Culvert Bottom n=.012
BC Design=,, 0 ,, 0 ,,,,,,

Type RM Length L Ch R = 1 ,8511.231,92.54,97.14,98.68
BEGIN DESCRIPTION:
Copy of 423s1u. XS 2/4
Bank offset = 4032
Manning's 'n' in channel reduced u/s and d/s of culvert to help with negative changes in profile
END DESCRIPTION:
XS GIS Cut Line= 5
     3154833.219    13934143.229     3154893.984    13933723.582
     3154926.358    13933206.961     3154960.882    13933100.741
     3155278.994     13931942.67
#Sta/Elev= 30
       0   61.52  271.72   60.37  365.39   58.81  427.26   59.86  676.31   59.93
  805.81   57.37  825.08   56.03  855.65   56.54  864.22   55.08  910.05   57.33
  914.06   60.87   937.8   60.32  945.31   57.88  959.37   50.22  962.99   47.24
     968    46.6  974.63   54.52  976.21   55.26  1004.2   62.19 1272.68   62.11
 1538.29   63.98 1834.39    61.5 1893.38   63.33 1960.25   63.16 1981.52   61.86
 2023.36   63.64 2110.71   62.69 2157.28   63.99 2180.62   62.81 2254.32   63.77
#Mann= 3 , 0 , 0
       0     .06       0   937.8     .03       0  1004.2     .06       0
#XS Ineff= 2 , 0
       0   937.8    59.5  1004.2       0    59.5
Permanent Ineff=
       F       F
Bank Sta=937.8,1004.2
XS Rating Curve= 0
Exp/Cntr=.5,.3

Type RM Length L Ch R = 1 ,8414.093,449.35,477.75,480.08
BEGIN DESCRIPTION:
Copy of 423s1u. XS 1/4
Bank offset = 4090
END DESCRIPTION:
XS GIS Cut Line= 5
     3154904.134    13934170.504     3154964.139    13933745.013
     3155005.871    13933219.385     3155046.665     13933132.91
     3155479.155    13932089.216
#Sta/Elev= 30
       0   61.32   83.52   61.26  109.43   59.94  204.71   59.07  255.71   60.33
  544.71   58.32  693.62    59.6  850.86   58.15  855.75   60.87  879.49   60.32
     887   57.88  901.06   50.22  904.68   47.24  909.69    46.6  916.32   54.52
   917.9   55.26  945.89   62.19 1047.53   61.17 1218.22   61.98 1330.27   60.35
 1380.03   62.43 1447.81    61.9 1536.31   64.07  1626.1   63.46 1675.13   61.51
  1707.6   62.55 1723.84   60.95 1743.72   62.72 1792.13   63.14 2182.35   63.67
#Mann= 3 , 0 , 0
       0     .06       0  879.49     .03       0  945.89     .06       0
Bank Sta=879.49,945.89
XS Rating Curve= 0
Exp/Cntr=.3,.1

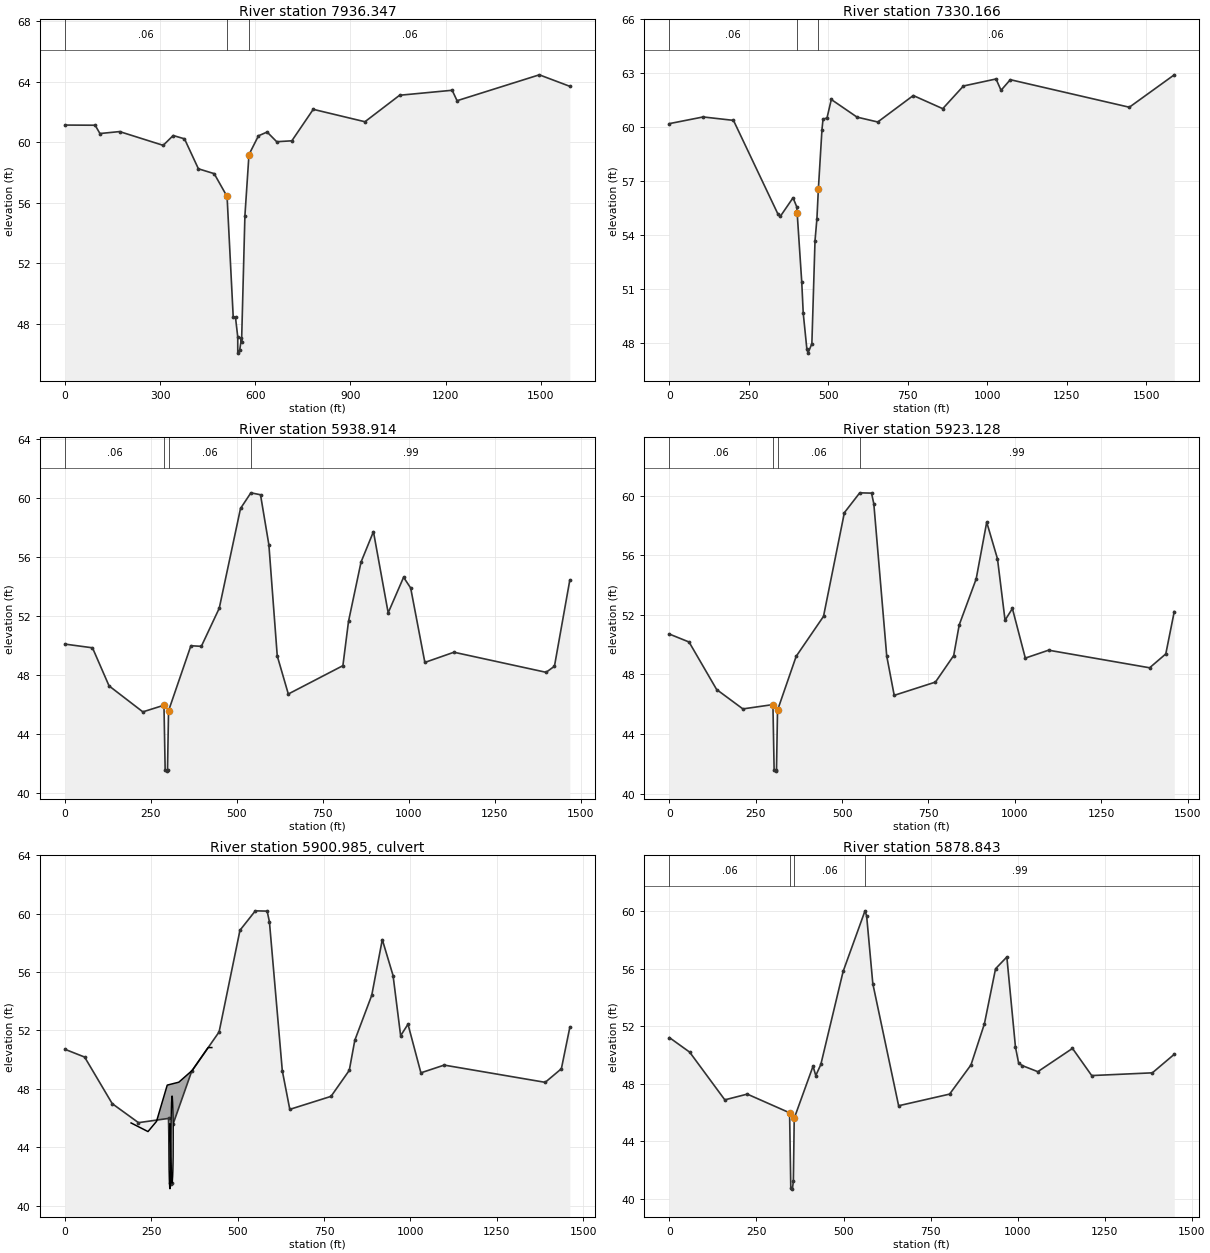
Type RM Length L Ch R = 1 ,7936.347,565.11,606.18,626.72
BEGIN DESCRIPTION:
423v2
Bank Station offset =      4455
END DESCRIPTION:
XS GIS Cut Line= 4
     3155010.922    13934055.077     3155289.674    13933675.271
     3155345.422    13933511.601     3155979.625    13932806.902
#Sta/Elev= 30
       0   61.13   95.01   61.12  110.05   60.57  172.06    60.7  309.55   59.79
  341.18   60.44  376.77   60.22  420.64   58.24  470.39   57.92  511.06   56.41
  530.41   48.45  537.64   48.42  544.72   47.13  544.82   46.06  550.98   46.27
  556.48   47.06  556.75   46.77  567.33   55.14  580.13   59.18  610.03   60.42
  637.33   60.67   667.6   60.03  715.35   60.09   782.8   62.17  945.87   61.35
 1055.18    63.1 1220.95   63.43 1236.41   62.74 1495.81   64.45 1592.08   63.69
#Mann= 3 , 0 , 0
       0     .06       0  511.06    .035       0  580.13     .06       0
Bank Sta=511.06,580.13
XS Rating Curve= 0
Exp/Cntr=.3,.1

Type RM Length L Ch R = 1 ,7330.166,1252.91,1391.25,1318.07
BEGIN DESCRIPTION:
423v3
Bank offset =    4558
channel reach length greater than both the  ROB and LOB reach length due to the sinuosity of the channel
END DESCRIPTION:
XS GIS Cut Line= 4
     3155318.716     13934274.15     3155595.335    13934096.669
     3155772.492    13934034.926     3156360.218    13933139.165
#Sta/Elev= 30
       0   60.21  106.04   60.58  201.36   60.39  341.62   55.17  349.21   55.07
  388.73   56.09  400.28   55.59  401.67   55.25  416.16   51.39  420.71   49.69
  432.05   47.71  435.85   47.46  447.93   47.99   457.8    53.7  463.82   54.93
  468.35   56.57   479.7   59.88  482.97   60.45  495.59   60.53  509.02   61.55
  590.05   60.57  655.12    60.3  766.87   61.77  859.52   61.04  924.65    62.3
 1027.12   62.69 1042.88   62.06 1071.97   62.65 1446.34   61.12 1587.63   62.92
#Mann= 3 , 0 , 0
       0     .06       0  401.67    .035       0  468.35     .06       0
Bank Sta=401.67,468.35
XS Rating Curve= 0
Exp/Cntr=.3,.1

Type RM Length L Ch R = 1 ,5938.914,25.09,15.79,17.64
BEGIN DESCRIPTION:
Copy of 423v4.  XS 4/4 for structure.
NOTES:  Adjusted elevations between channel banks by 1.455 ft. Set Cont.\ Exp Coeff. to 0.3 & 0.5.Adjust elevations as needed.
Bank Station offset =      4704
The xsec crosses a pond on the ROB. Hence Blocked
END DESCRIPTION:
XS GIS Cut Line= 5
     3156599.134    13934792.781     3156679.743    13934742.673
      3156823.91    13934605.581     3156896.854    13934511.711
     3157664.683    13933786.894
#Sta/Elev= 30
       0   50.12   79.89   49.87   128.1   47.29  226.42   45.53  287.85   45.98
  291.32  41.565  295.74  41.515  298.16  41.585  301.16    45.6  366.16   50.01
  396.58   49.97  448.64   52.55  510.53   59.31  540.68   60.37  568.71   60.24
  593.04   56.85  617.41   49.32  649.59   46.74  808.41   48.66  824.72   51.66
  861.19   55.68  897.27   57.74  940.13   52.24  984.96   54.65 1005.59   53.92
 1046.84   48.88  1131.5   49.57 1399.52   48.21 1423.85   48.62 1468.63   54.47
#Mann= 4 ,-1 , 0
       0     .06       0  287.85    .035       0  301.16     .06       0
  540.68     .99       0
#Block Obstruct= 2 , 0
       0                    1010       0      53
Bank Sta=287.85,301.16
XS Rating Curve= 0
Exp/Cntr=.5,.3

Type RM Length L Ch R = 1 ,5923.128,27.71,44.28,50.6
BEGIN DESCRIPTION:
Copy of 423v4.  XS 3/4 for structure.
NOTES: Adjusted elevations between channel banks by 1.455 ft. Set Cont.\ Exp Coeff. to 0.3 & 0.5.Adjust elevations as needed.
Bank Station offset =      4692
The xsec crosses a pond on the ROB. Hence Blocked
END DESCRIPTION:
XS GIS Cut Line= 5
     3156604.587     13934817.32      3156698.99    13934760.454
     3156864.232    13934585.701      3156916.64    13934516.422
     3157679.011    13933832.741
#Sta/Elev= 30
       0   50.71   56.73   50.18  136.67   46.99  212.65   45.69  299.63   45.98
   303.1  41.565  307.52  41.515  309.94  41.585  312.94    45.6  366.95   49.22
  446.08    51.9  506.52   58.86  551.02   60.19  585.13   60.17  591.76   59.45
  629.11   49.24  650.78    46.6  770.15   47.49     823   49.27  839.02   51.33
  888.07   54.41   918.6   58.22  949.78   55.76  971.72   51.64  992.96   52.43
 1030.37    49.1 1097.77   49.63 1390.31   48.45 1437.11   49.38 1461.61   52.22
#Mann= 4 ,-1 , 0
       0     .06       0  299.63    .035       0  312.94     .06       0
  551.02     .99       0
#XS Ineff= 2 , 0
       0     298   45.08     315       0   45.08
Permanent Ineff=
       F       F
#Block Obstruct= 2 , 0
       0                     960       0      53
Bank Sta=299.63,312.94
XS Rating Curve= 0
Exp/Cntr=.5,.3

Type RM Length L Ch R = 2 ,5900.985,,,
BEGIN DESCRIPTION:
423s2: Gravel Rd. North of Baker Rd. ( 2 RCP Culverts  1-54" Dia. & 1- 72" Dia )
NOTES: Extended road deck at US x-sec to left to x-sec station 425
Downstream invert elevation for the 4.5 ft RCP culvert was assumed to be approximately the same elevation as the 6 ft RCP culvert since there is no DS invert elevation data provided in the survey notes.
Type of flow set to pressure/weir.
END DESCRIPTION:
Bridge Culvert--1,0,-1,-1, 0
Deck Dist Width WeirC Skew NumUp NumDn MinLoCord MaxHiCord MaxSubmerge Is_Ogee
17.142,10,2.6,0, 8, 7, 45.08, , .95, 0, 0,0,,
  191.24  240.19  264.95  295.89  329.45  368.41   414.2     425
   45.67   45.08   45.78   48.26   48.46   49.27   50.83   50.83
                                                                
  236.73  285.68  310.44  341.38  374.94   413.9  459.69
   45.67   45.08   45.78   48.26   48.46   49.27   50.83
                                                        
BR Coef=-1 , 0 , 0 ,, 0 ,,,.8,0,,0,
WSPro=,,,, 1 ,,,, 0 ,,,, 0 ,,,,-1 ,-1 ,-1 , 0 , 0 , 0 , 0 , 0
Culvert=1,4.5,,27,.012,.5,1,1,1,41.14,303.77,40.49,349.26,RCP-4.5ft   , 0 ,8.642
Culvert Bottom n=.012
Culvert=1,6,,27,.012,.5,1,1,1,41.53,310.02,40.49,355.51,RCP-6ft     , 0 ,8.642
Culvert Bottom n=.012
BC Design=,, 0 ,, 0 ,,,,,,

Type RM Length L Ch R = 1 ,5878.843,26.04,20.78,15.11
BEGIN DESCRIPTION:
Copy of 423v4.  XS 2/4 for structure.
NOTES: Adjusted elevations between channel banks by 2.3 ft. Set Cont.\ Exp Coeff. to 0.3 & 0.5.   Adjust elevations as needed.
Bank Station offset =      4647
The xsec crosses a pond on the ROB. Hence Blocked
END DESCRIPTION:
XS GIS Cut Line= 5
     3156599.134    13934847.313     3156794.153    13934723.708
     3156920.362    13934582.372     3157345.581    13934192.155
     3157687.607    13933895.782
#Sta/Elev= 30
       0   51.21    58.1    50.2  159.06   46.88  223.56   47.28  345.12   45.98
  348.59   40.72  353.01   40.67  355.96   41.21  358.43    45.6  412.44   49.22
  420.38   48.57  434.82   49.34  498.84   55.81  561.77   60.03  566.42   59.68
  584.21   54.96  658.33   46.47  804.75   47.28  866.13   49.31  904.74   52.17
  936.75      56  969.17   56.82  993.96   50.55 1003.11   49.43 1013.89   49.26
 1058.11   48.84 1157.76   50.46 1212.96   48.57 1387.19   48.76 1450.08   50.05
#Mann= 4 ,-1 , 0
       0     .06       0  345.12    .035       0  358.43     .06       0
  561.77     .99       0
#XS Ineff= 2 , 0
       0     345   45.08     360       0   45.08
Permanent Ineff=
       F       F
#Block Obstruct= 2 , 0
       0                     970       0      53
Bank Sta=345.12,358.43
XS Rating Curve= 0
Exp/Cntr=.5,.3

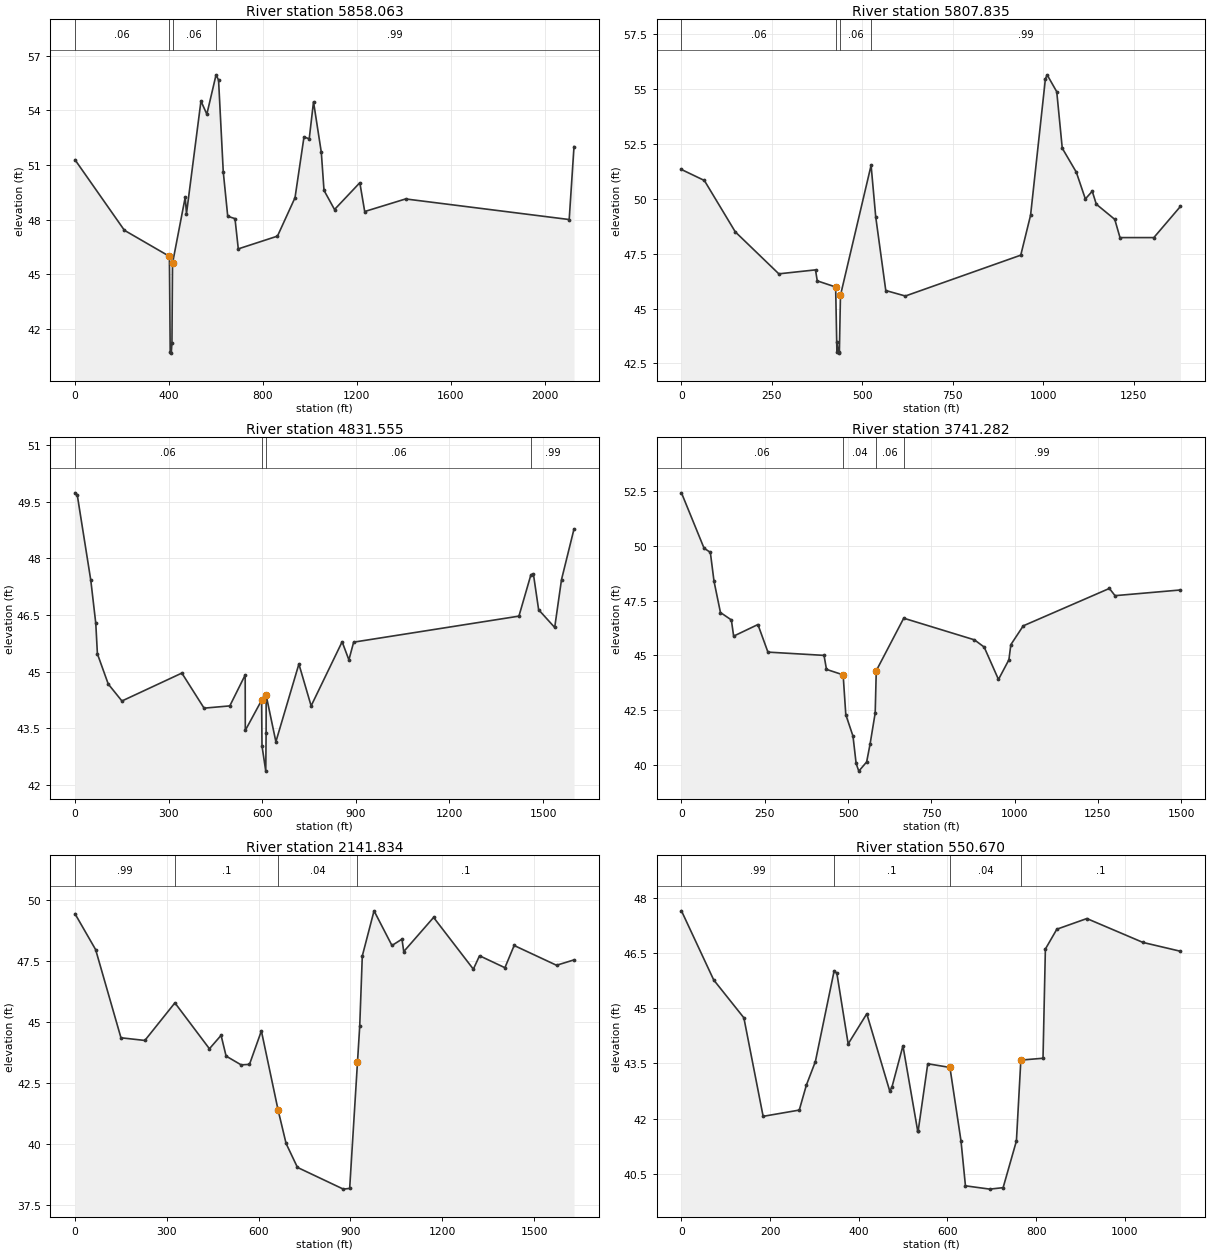
Type RM Length L Ch R = 1 ,5858.063,30.11,50.23,56.8
BEGIN DESCRIPTION:
Copy of 423v4.  XS 1/4 for structure.
NOTES: Adjusted elevations between channel banks by 2.3 ft. Extended ROB to elev 52' at distance of 657.45'
Adjust elevations as needed.
Bank Station offset =      4590
The xsec crosses a pond on the ROB. Hence Blocked
END DESCRIPTION:
XS GIS Cut Line= 6
     3156580.048    13934890.938     3156582.775    13934885.485
     3156756.465    13934776.472     3156808.286    13934747.263
     3156942.578    13934580.636 3158234.290410113933571.1862022
#Sta/Elev= 30
       0   51.28  210.24   47.41  401.84   45.98  405.31   40.72  409.73   40.67
  412.68   41.21  415.15    45.6  469.16   49.22  474.63   48.33  536.18    54.5
  561.23   53.78  600.45   55.94  611.13   55.65   631.1   50.62  650.13   48.18
  681.03   48.05  695.06   46.39  861.87   47.09  936.58    49.2  974.73   52.53
  997.02   52.43 1015.28   54.46 1048.43   51.69 1059.95    49.6 1104.69   48.55
 1212.42   50.02 1233.16   48.44 1407.38   49.13 2103.58      48 2124.02      52
#Mann= 4 ,-1 , 0
       0     .06       0  401.84    .035       0  415.15     .06       0
  600.45     .99       0
#Block Obstruct= 2 , 0
       0                    1030       0      50
Bank Sta=401.84,415.15
XS Rating Curve= 0
Exp/Cntr=.3,.1

Type RM Length L Ch R = 1 ,5807.835,898.9,976.28,981.43
BEGIN DESCRIPTION:
423v4.  Surveyed section.
Bank Station offset =      4566
The xsec crosses a pond on the ROB. Hence Blocked
END DESCRIPTION:
XS GIS Cut Line= 5
     3156590.954     13934912.75     3156774.367    13934799.085
     3156835.031    13934758.807     3156979.198    13934621.715
     3157719.128    13934125.022
#Sta/Elev= 30
       0   51.33   63.27   50.83  148.78   48.49  269.04   46.58  370.37   46.76
  375.19   46.26  426.02   45.98  429.49   43.02  429.83   43.49  433.91   42.97
  436.33   43.04  439.33    45.6  523.95   51.52  536.76   49.17  564.53   45.82
  618.62   45.57  937.49   47.43  964.61   49.25 1005.56   55.46 1010.32   55.64
 1036.89   54.87 1052.13    52.3 1090.89   51.21 1115.95   49.99 1135.01   50.34
 1146.16   49.75 1197.18   49.06 1211.64   48.23 1305.17   48.23 1378.72   49.65
#Mann= 4 ,-1 , 0
       0     .06       0  426.02    .035       0  439.33     .06       0
  523.95     .99       0
#Block Obstruct= 2 , 0
       0                    1140       0    49.5
Bank Sta=426.02,439.33
XS Rating Curve= 0
Exp/Cntr=.3,.1

Type RM Length L Ch R = 1 ,4831.555,1108.16,1090.27,949.93
BEGIN DESCRIPTION:
423v5
Notes: Extended LOB to elev 48' at distance of 26.6'
Bank Station offset =      4389
small depression area appears in ROB, ineffective but available
END DESCRIPTION:
XS GIS Cut Line= 6
     3156710.131    13935594.745     3156973.707    13935564.936
     3157260.259     13935506.21     3157329.944     13935480.29
     3158210.508    13935149.952     3158235.413    13935140.609
#Sta/Elev= 30
       0   49.74    7.32   49.68   50.66   47.42    66.6   46.28   71.84   45.47
  106.55   44.67  150.43   44.22  342.47   44.96  413.67   44.03  496.15   44.09
  545.44   44.91   545.8   43.44   598.1   44.24   599.3   43.03  611.39   42.36
  612.47   43.36  612.68   44.37  643.81   43.14  717.56    45.2  756.78   44.09
  856.11   45.79  877.79   45.31  893.05   45.78 1422.71   46.47 1461.22   47.57
 1469.24   47.58 1485.84   46.64 1537.35   46.17  1559.2   47.44  1599.2   48.78
#Mann= 4 ,-1 , 0
       0     .06       0   598.1     .04       0  612.68     .06       0
 1461.22     .99       0
#Block Obstruct= 2 , 0
       0                 1461.22       0   47.57
Bank Sta=598.1,612.68
XS Rating Curve= 0
Exp/Cntr=.3,.1

Type RM Length L Ch R = 1 ,3741.282,1753.55,1599.45,1590.28
BEGIN DESCRIPTION:
423v6
Bank Station offset =      4468
END DESCRIPTION:
XS GIS Cut Line= 4
     3157160.827    13936567.834     3157528.697    13936406.001
     3157688.596    13936347.527     3158558.561    13936030.548
#Sta/Elev= 30
       0   52.43   67.84    49.9    86.7   49.71   97.72   48.39  117.05   46.96
  149.82   46.62  156.66   45.88  229.55   46.41  259.57   45.15  428.04      45
  435.37   44.36  485.37   44.11  493.37   42.29  514.95   41.31  524.37   40.06
  532.43   39.71  555.97   40.13  566.43   40.96  581.62   42.37  584.84    44.3
  667.26    46.7  879.58   45.71  908.76   45.38  951.72    43.9  983.03    44.8
  988.85   45.49 1026.03   46.35 1284.68   48.06 1301.64   47.73 1498.06   47.99
#Mann= 4 ,-1 , 0
       0     .06       0  485.37     .04       0  584.84     .06       0
  667.26     .99       0
Bank Sta=485.37,584.84
XS Rating Curve= 0
Exp/Cntr=.3,.1

Type RM Length L Ch R = 1 ,2141.834,1638.06,1591.16,1591.16
BEGIN DESCRIPTION:
423v7
Bank Station offset =      4123
It appears from MrSids LOB area is backwater area, therefore ineffective
END DESCRIPTION:
XS GIS Cut Line= 4
     3158690.531    13937520.636     3158827.683    13936867.595
     3158955.808    13936661.407     3159120.309    13935960.049
#Sta/Elev= 30
       0   49.45   67.47   47.98  150.18   44.37  228.24   44.26  326.45    45.8
  439.24   43.92  477.34   44.47  493.72   43.62  542.89   43.26   570.1   43.28
  609.02   44.65  663.59   41.41  689.73   40.04  726.84   39.06  876.83   38.17
  897.48    38.2     923   43.37  930.34   44.85  938.72   47.72   977.1   49.57
 1035.63   48.15 1068.35   48.41 1074.17    47.9 1171.68    49.3 1301.59   47.18
 1321.74   47.73  1404.7   47.24  1434.9   48.15 1573.33   47.34 1630.43   47.56
#Mann= 4 ,-1 , 0
       0     .99       0  326.45      .1       0  663.59     .04       0
     923      .1       0
Bank Sta=663.59,923
XS Rating Curve= 0
Exp/Cntr=.3,.1

Type RM Length L Ch R = 1 ,550.670 ,626.41,550.67,522.79
BEGIN DESCRIPTION:
423v8
Bank Station offset =      4304
It appears from MrSids LOB area is backwater area, therefore ineffective
END DESCRIPTION:
XS GIS Cut Line= 4
     3160010.809    13937203.283     3160175.981    13936655.961
     3160191.205    13936431.208     3160251.581    13936108.046
#Sta/Elev= 30
       0   47.65   72.75   45.77   140.8   44.74  184.24   42.06  265.76   42.23
  281.81   42.91  302.14   43.55  344.49   46.02  350.61   45.95  376.09   44.03
  418.08   44.85  469.83   42.75  474.73   42.85  499.66   43.98  532.82   41.67
  533.98   41.66  555.64   43.49  605.64   43.39  630.64   41.39  640.64   40.17
  695.64   40.08  725.64   40.12  755.64   41.39  765.64   43.59  815.64   43.64
  820.98   46.61  846.82   47.15  914.54   47.44 1041.19   46.79 1125.72   46.55
#Mann= 4 ,-1 , 0
       0     .99       0  344.49      .1       0  605.64     .04       0
  765.64      .1       0
Bank Sta=605.64,765.64
XS Rating Curve= 0
Exp/Cntr=.3,.1

Chan Stop Cuts=-1